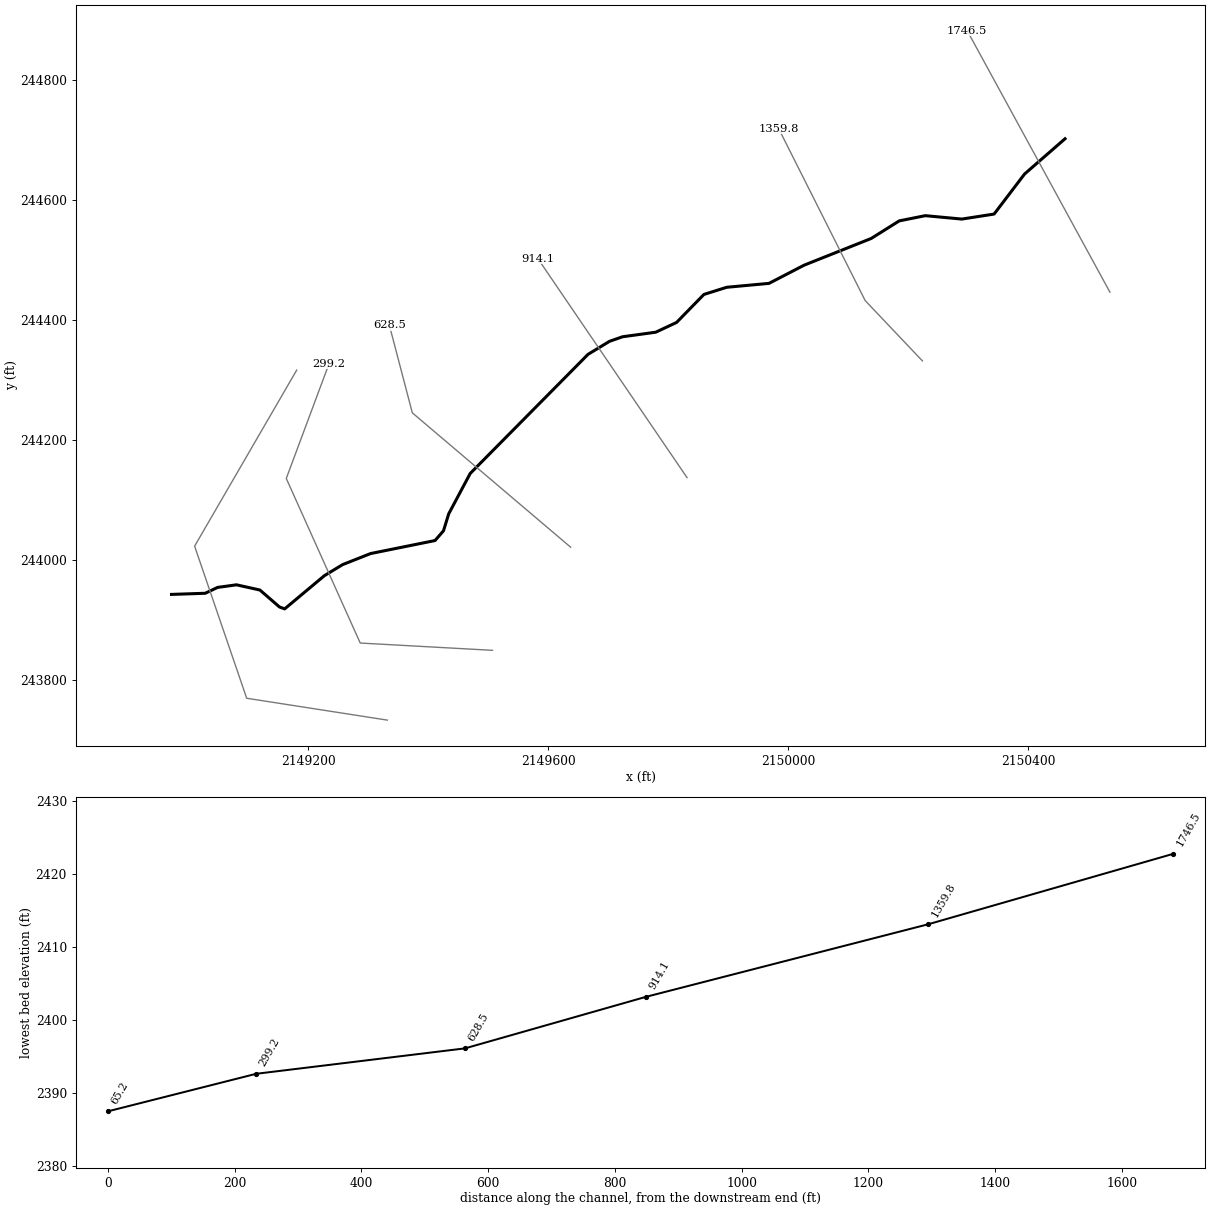
--- ARCHERFK.prj (project) ---

Proj Title=ARCHERFK
Current Plan=p01
Default Exp/Contr=0,0
English Units
Geom File=g01
Flow File=f01
Plan File=p01
BEGIN DESCRIPTION:
END DESCRIPTION:
DSS Export Rating Curves= 0
DSS Export Rating Curve Sorted= 0
DSS Export Volume Flow Curves= 0
DXF OffsetX= 0
DXF OffsetY= 0
DXF ScaleX= 0
DXF ScaleY= 0

--- ARCHERFK.p01 (plan) ---

Plan Title=Floodplain
Program Version=4.00
Geom File=g01
Flow File=f01
K Sum by GR=0
Std Step Tol=0.01
Critical Tol=0.01
Num of Std Step Trials=20
Max Error Tol=0.3
Flow Tol Ratio=0.001
Split Flow NTrial=30
Split Flow Tol=0.02
Split Flow Ratio=0.02
Log Output Level=0
Friction Slope Method=1
Unsteady Friction Slope Method=2
Unsteady Bridges Friction Slope Method=1
Global Log Level=0
CheckData=False
Run HTab=0
Run UNet=0
Run PostProcess=0
UNET Theta=0
UNET Theta Warmup=0
UNET ZTol=0
UNET ZSATol=0
UNET MxIter=0
UNET MaxInSteps=0
UNET DtIC=0
UNET DtMin=0
UNET MaxCRTS=0
UNET WFStab=0
UNET SFStab=0
UNET WFX=0
UNET SFX=0
UNET DSS MLevel=0
UNET DZMax Abort=0
UNET Convert EG Bridges=0
UNET Use Existing IB Tables=0
UNET Froude Limit=0
UNET Froude Power=0
Write IC File=0
Echo Input=False
Echo Output=False
Write Detailed=0

--- ARCHERFK.f01 (steady flow) ---

Flow Title=2010 USGS WV Regression Equation
Program Version=4.00
Number of Profiles=1
Profile Names=P100yr
River Rch & RM=ARCHERFK,Main      ,1746.5
520.1705
River Rch & RM=ARCHERFK,Main      ,628.5
535.8181
River Rch & RM=ARCHERFK,Main      ,299.2
539.6387
Boundary for River Rch & Prof#=ARCHERFK,Main      ,1
Up Type=0
Dn Type=3
Dn Slope=0.018763

--- ARCHERFK.g01 (geometry) ---

Geom Title=LiDAR
Program Version=4.10

River Reach=ARCHERFK        ,Main
Reach XY= 30
     2150461.344      244702.386     2150393.959      244643.686
     2150343.123      244576.874     2150289.383      244568.523
     2150228.413      244574.192      2150185.01      244565.511
     2150138.352      244536.214      2150026.59      244491.726
     2149967.996      244461.344     2149897.467      244454.834
      2149859.49      244442.898     2149813.916       244396.24
     2149779.194      244379.964     2149723.856      244372.369
     2149702.154      244364.773     2149666.347      244343.072
      2149469.95      244144.504     2149434.142       244077.23
     2149425.462      244049.018     2149411.356      244032.742
     2149303.934      244011.041     2149257.276      243992.594
     2149226.894      243974.148     2149160.705       243918.81
     2149152.024      243922.065     2149119.472      243950.277
      2149080.41      243958.957     2149048.943      243954.617
     2149028.326      243944.851     2148972.152      243942.976

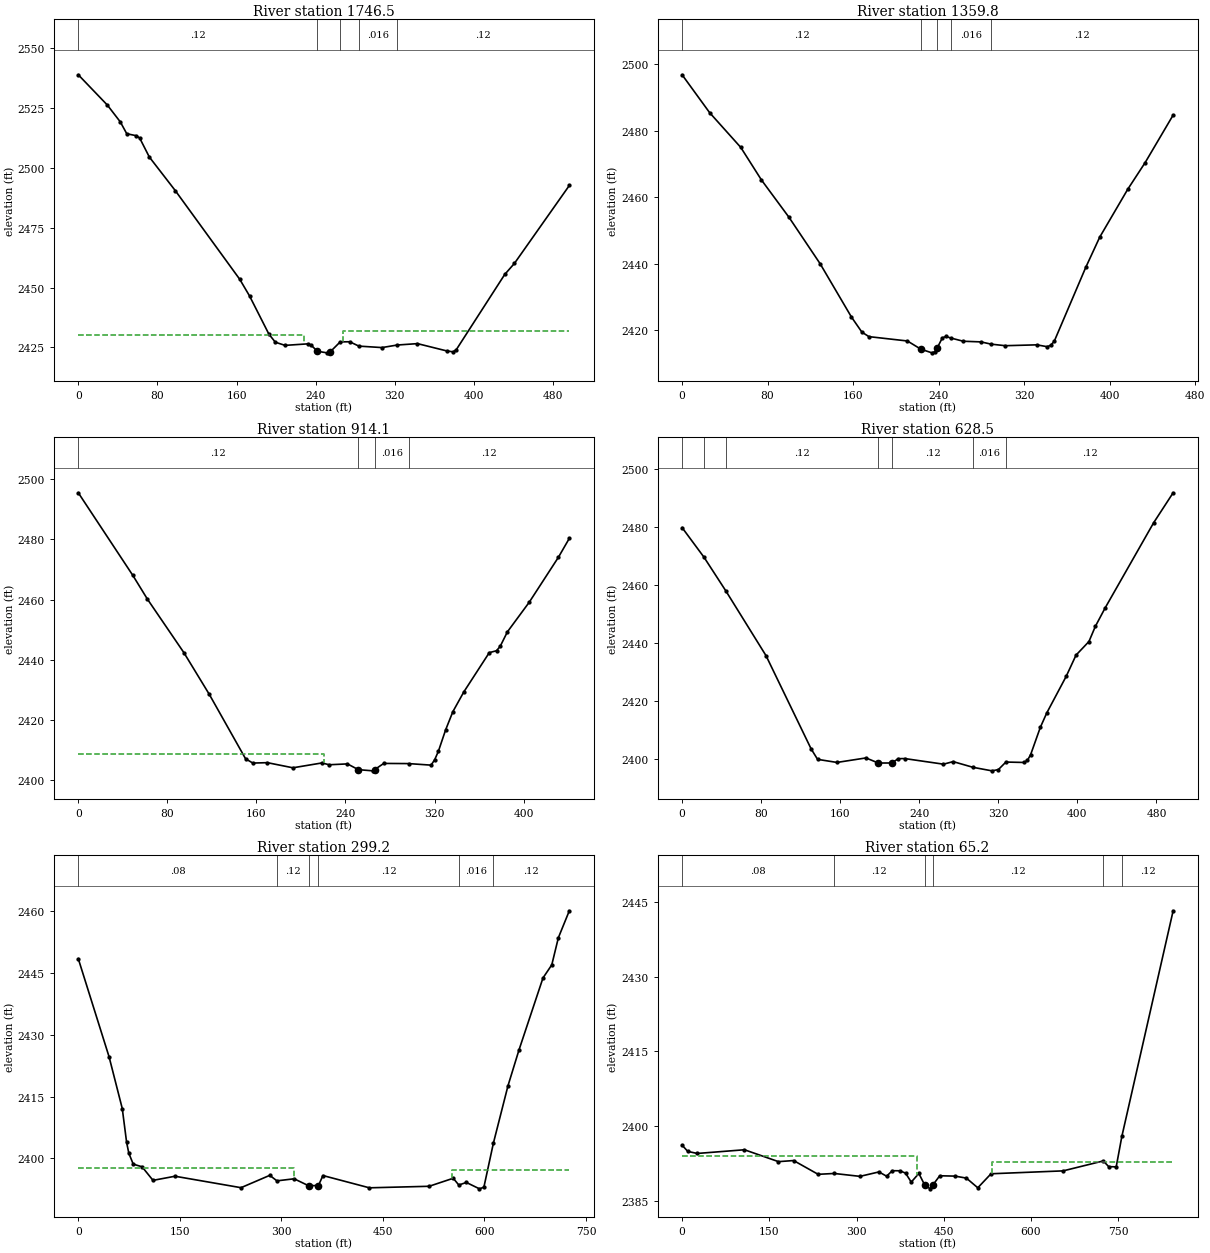
Type RM Length L Ch R = 1 ,1746.5  ,387.4,386.7,384.3
XS GIS Cut Line= 2
     2150536.191      244446.636     2150298.344        244882.4
#Sta/Elev= 30
       0 2538.93    29.4 2526.27    42.5 2519.23      49  2514.3    58.8 2513.46
    62.1 2512.47    71.8 2504.58      98 2490.57   163.3 2453.43   173.1 2446.54
   192.7 2430.56   199.2 2427.19     209 2425.87   231.9  2426.5   235.2 2426.03
   241.72423.407   251.5 2422.75   254.8 2423.22   264.82427.328   274.4 2427.38
  283.652425.558     307 2424.95  322.432426.015   342.9  2426.6   372.3 2423.57
   378.9 2423.17   382.1 2424.05   431.1  2455.5   440.9 2460.12   496.4 2492.67
#Mann= 5 ,-1 , 0
       0     .12       0   241.7    .045       0   264.8     .12       0
  283.65    .016       0  322.43     .12       0
#XS Ineff= 2 , 0
          228.59 2430.14  267.29         2431.76
Permanent Ineff=
       F       F
Bank Sta=241.7,254.8
XS Rating Curve= 0 ,0
Exp/Cntr=0.3,0.1

Type RM Length L Ch R = 1 ,1359.8  ,442.1,445.7,448.1
XS GIS Cut Line= 3
     2150223.691      244332.053     2150128.205      244432.747
     2149984.108      244719.206
#Sta/Elev= 30
       0 2496.86    25.8 2485.43    54.9 2474.98    74.2 2465.19     100 2453.93
   129.1 2439.96   158.4  2423.9   168.2 2419.34   174.8 2417.98   210.8 2416.67
   223.4  2414.2   233.7  2413.1   236.9 2413.47   238.4 2414.41   243.5 2417.62
   246.8 2418.03  251.522417.551   263.1 2416.59   279.5  2416.4  289.312415.709
   302.4 2415.25   331.8 2415.51   341.6 2414.95   344.9 2415.39   348.2 2416.61
   377.6 2438.81   390.7 2447.94   416.9 2462.36   433.2  2470.4   459.4 2484.72
#Mann= 5 ,-1 , 0
       0     .12       0   223.4    .045       0   238.4     .12       0
  251.52    .016       0  289.31     .12       0
Bank Sta=223.4,238.4
XS Rating Curve= 0 ,0
Exp/Cntr=0.3,0.1

Type RM Length L Ch R = 1 ,914.1   ,279.3,285.6,291.5
XS GIS Cut Line= 2
      2149831.33      244137.608     2149583.066      244502.192
#Sta/Elev= 30
       0 2495.41      49    2468    62.1 2460.12    94.8  2442.4   117.6 2428.58
   150.3 2407.14   156.8 2405.73   169.9 2405.86   192.8 2404.16   218.9 2405.77
   225.4 2405.17   241.8 2405.45   251.6 2403.54   264.6 2403.15  266.172403.545
   274.4 2405.61  296.672405.555   316.9 2405.04   320.2 2406.87   323.5 2409.66
     330 2416.76   336.5 2422.79   346.3 2429.32   369.2 2442.37   375.7    2443
     379 2444.46   385.5 2449.28   405.1  2459.1   431.3 2474.01   441.1 2480.29
#Mann= 4 ,-1 , 0
       0     .12       0   251.6    .045       0  266.17    .016       0
  296.67     .12       0
#XS Ineff= 2 , 0
          220.33 2408.78
Permanent Ineff=
       F       F
Bank Sta=251.6,266.17
XS Rating Curve= 0 ,0
Exp/Cntr=0.3,0.1

Type RM Length L Ch R = 1 ,628.5   ,339.5,329.3,318.4
XS GIS Cut Line= 3
     2149637.377      244021.636     2149373.488      244245.595
     2149335.294      244391.428
#Sta/Elev= 30
       0 2479.73   22.16 2469.55   44.212457.993    84.9 2435.71   130.6 2403.61
   137.1 2400.04   156.7 2398.98   186.1 2400.53   198.5 2398.78   212.2 2398.79
   218.8 2400.28   225.3 2400.31   264.5 2398.38   274.3 2399.26  294.462397.293
   313.5 2396.09     320 2396.51  327.662399.111   346.1 2398.97   349.4 2399.67
   352.7 2401.66   362.5 2411.04     369 2415.99   388.7  2428.6   398.6 2435.87
   411.7 2440.56   418.2 2445.78     428 2452.06   477.2 2481.42   496.9 2491.71
#Mann= 7 ,-1 , 0
       0     .12       0   22.16     .08       0   44.21     .12       0
   198.5    .045       0   212.2     .12       0  294.46    .016       0
  327.66     .12       0
Bank Sta=198.5,212.2
XS Rating Curve= 0 ,0
Exp/Cntr=0.3,0.1

Type RM Length L Ch R = 1 ,299.2   ,236.6,234,228.1
XS GIS Cut Line= 4
     2149507.169      243849.761     2149286.683      243861.914
     2149163.419       244136.22     2149234.599      244327.192
#Sta/Elev= 30
       0  2448.5    45.5 2424.67      65  2412.1    71.4 2403.89    74.7 2401.24
    81.2  2398.6    94.2 2397.97   110.4 2394.67   142.9 2395.67   240.4 2392.89
   282.9 2395.89  293.43 2394.55   318.9 2395.05  340.182393.368   354.8 2393.42
   361.4 2395.84     430 2392.86   518.3 2393.23   553.9 2395.18  562.12 2393.54
   573.3 2394.16   592.7 2392.61   599.2 2393.02   613.32403.753   634.8 2417.65
     651 2426.32   686.5 2443.83   699.5 2447.01   709.2 2453.59   725.4 2460.14
#Mann= 6 ,-1 , 0
       0     .08       0  293.43     .12       0  340.18    .045       0
   354.8     .12       0  562.12    .016       0   613.3     .12       0
#XS Ineff= 2 , 0
          318.36 2397.59   551.5          2397.3
Permanent Ineff=
       F       F
Bank Sta=340.18,354.8
XS Rating Curve= 0 ,0
Exp/Cntr=0.3,0.1

Type RM Length L Ch R = 1 ,65.2    ,71.8,65.2,57.6
XS GIS Cut Line= 4
     2149331.822      243733.442     2149097.447        243769.9
     2149010.641      244023.372      2149180.78      244316.775
#Sta/Elev= 30
       0 2396.22     9.8 2394.97      26 2394.56   107.2  2395.3   165.7 2392.92
   191.7 2393.14   233.9 2390.38  261.59 2390.55   305.8 2389.97   338.5 2390.86
   351.6    2390   361.4  2391.1   374.4 2391.09   384.2 2390.62     394 2388.82
   407.1 2390.55   416.9 2388.28   426.7 2387.47  431.662388.321     443 2390.09
   469.2 2390.02   488.8 2389.62   508.4 2387.68   531.2 2390.49   655.1 2391.07
   724.2 2393.06   733.4 2391.93   746.4 2391.87  756.132397.986   844.3 2443.19
#Mann= 6 ,-1 , 0
       0     .08       0  261.59     .12       0   416.9    .045       0
  431.66     .12       0   724.2    .016       0  756.13     .12       0
#XS Ineff= 2 , 0
          403.52    2394  533.54         2392.89
Permanent Ineff=
       F       F
Bank Sta=416.9,431.66
XS Rating Curve= 0 ,0
Exp/Cntr=0.3,0.1

Chan Stop Cuts=-1
Use User Specified Reach Order=0
Composite Channel Slope=5